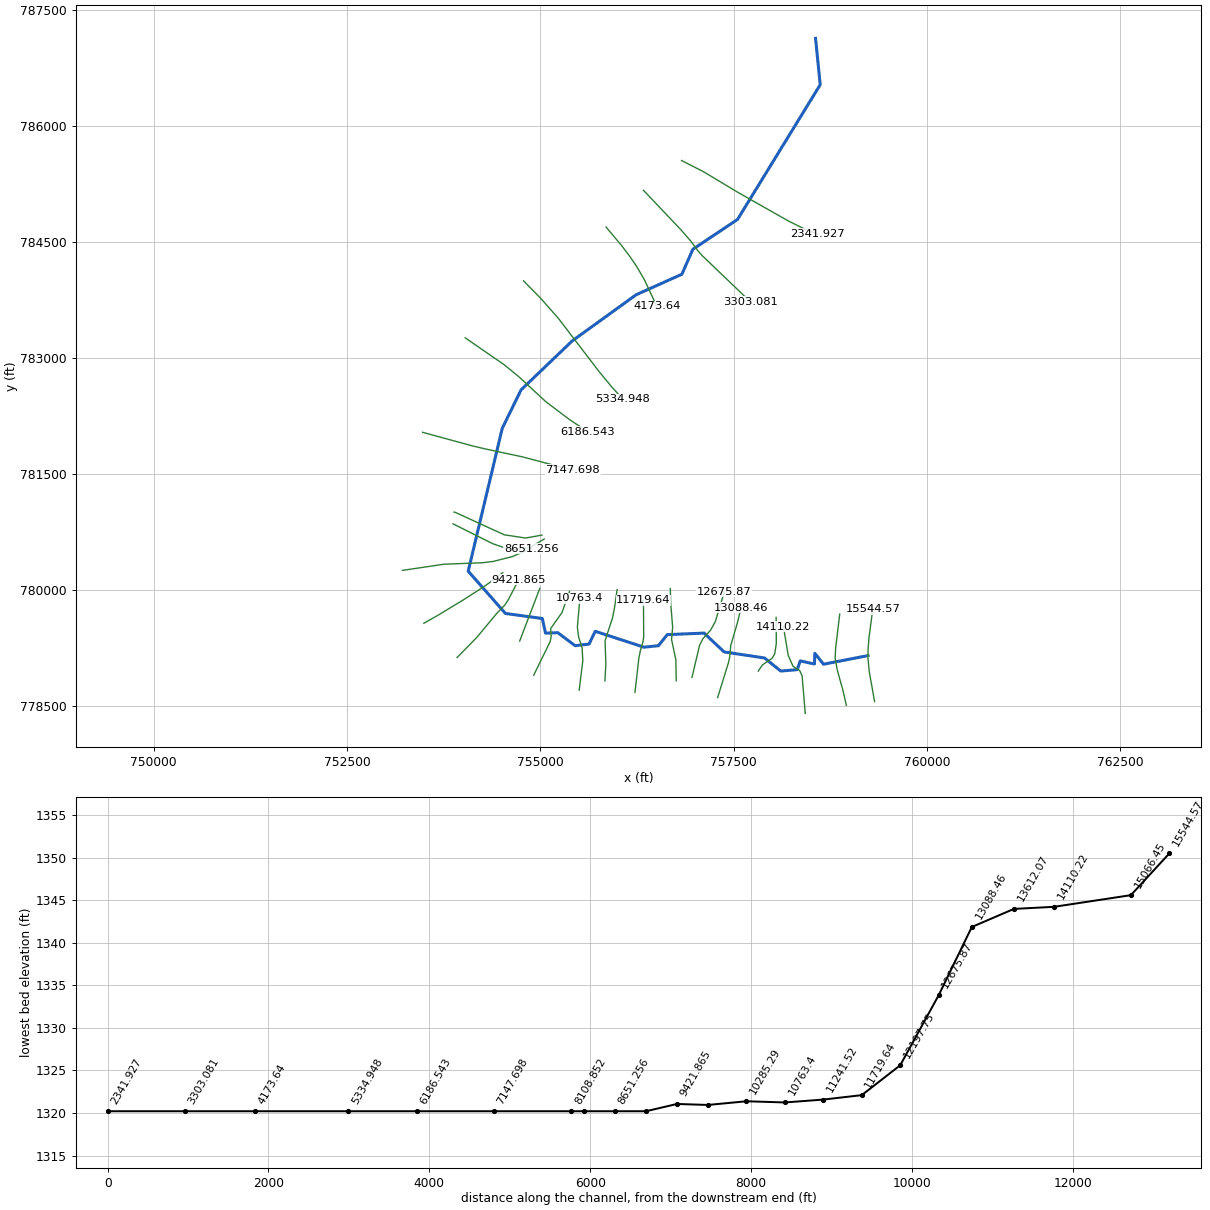
--- 15363_ras.prj (project) ---

Proj Title=15363
Current Plan=p01
Default Exp/Contr=0.3,0.1
English Units
Geom File=g01
Flow File=f01
Plan File=p01
Y Axis Title=Elevation
X Axis Title(PF)=Main Channel Distance
X Axis Title(XS)=Station
BEGIN DESCRIPTION:
RFD model 15363 exported to HEC-RAS
END DESCRIPTION:

--- 15363_ras.p01 (plan) ---

Plan Title=Plan 01
Program Version=4.10
Short Identifier=Plan 01
Geom File=g01
Flow File=f01
Subcritical Flow
Calc Critical at every XS
Secant Critical Depth

--- 15363_ras.f01 (steady flow) ---

Flow Title=Flow 01
Program Version=5.01
Number of Profiles= 6
Profile Names=10yr,25yr,50yr,100yr,100plus,500yr
River Rch & RM=15363,23,15544.57
  769.35 1251.88 1716.49  2280.9 3620.42  4060.5
River Rch & RM=15363,23,15066.45
  790.36 1285.97 1763.13 2342.77 3718.62 4170.22
River Rch & RM=15363,23,14110.22
  897.66 1460.05 2001.28  2658.6 4219.94 4730.19
River Rch & RM=15363,23,13612.07
  906.17 1473.85 2020.17 2683.64 4259.68 4774.57
River Rch & RM=15363,23,13088.46
  981.05 1595.29 2186.27 2903.87 4609.26 5164.88
River Rch & RM=15363,23,12675.87
 1143.53 1858.72 2546.49 3381.39 5367.21 6010.78
River Rch & RM=15363,23,12197.75
  1155.7 1878.45 2573.47 3417.15 5423.98 6074.12
River Rch & RM=15363,23,11719.64
 1202.11 1953.67  2676.3 3553.44 5640.31 6315.46
River Rch & RM=15363,23,11241.52
 1270.98 2065.29 2828.89 3755.66 5961.27 6673.47
River Rch & RM=15363,23, 10763.4
 1280.55 2080.79 2850.08 3783.74 6005.86 6723.19
River Rch & RM=15363,23,10285.29
 1329.73 2160.48 2959.01 3928.09 6234.97  6978.7
River Rch & RM=15363,23, 9807.17
 1346.78  2188.1 2996.76 3978.11 6314.37 7067.24
River Rch & RM=15363,23,9421.865
 1883.08 3056.62 4183.41 5549.98 8809.36 9847.46
River Rch & RM=15363,23, 9036.56
 2070.37 3359.76 4597.41 6098.17 9679.4910816.33
River Rch & RM=15363,23,8651.256
 2074.48 3366.42  4606.5  6110.2 9698.5910837.59
River Rch & RM=15363,23,8265.951
 2131.44 3458.59 4732.36 6276.84 9963.0911132.04
River Rch & RM=15363,23,8108.852
 2132.89 3460.94 4735.57 6281.08 9969.8311139.54
River Rch & RM=15363,23,7147.698
 2493.03  4043.6 5531.06 7334.13 11641.3 12999.6
River Rch & RM=15363,23,6186.543
 2648.16 4294.49 5873.53 7787.3812360.7513799.91
River Rch & RM=15363,23,5334.948
 2810.03 4556.26 6230.79 8260.17 13111.214634.51
River Rch & RM=15363,23, 4173.64
  2944.3 4773.37 6527.07 8652.2213733.4915326.45
Boundary for River Rch & Prof#=15363,23,1
Up Type= 0
Dn Type= 2
Boundary for River Rch & Prof#=15363,23,2
Up Type= 0
Dn Type= 2
Boundary for River Rch & Prof#=15363,23,2
Up Type= 0
Dn Type= 2
Boundary for River Rch & Prof#=15363,23,2
Up Type= 0
Dn Type= 2
Boundary for River Rch & Prof#=15363,23,2
Up Type= 0
Dn Type= 2
Boundary for River Rch & Prof#=15363,23,2
Up Type= 0
Dn Type= 2

--- 15363_ras.g01 (geometry) ---

Geom Title=15363
Program Version=4.10

River Reach=15363,23
Reach XY= 30
 759237.61494863779155.273091853758662.434727192779043.897432342
758550.455560505779184.522432342758545.247227162779046.501598984
758361.653477192779086.866182327758322.590977162778973.584932342
758109.049310505778955.355765641757899.413893849779124.626598969
757377.278477162779202.751598999757118.163893878779446.241182342
756641.601393849779426.709932327756527.018060535779283.480765671
756340.820143849779263.949515656755710.611810535779469.678682342
755629.882643908779304.314098999755450.195143878779283.480765671
755226.236810535779451.449515656755067.382643849779446.241182342
755025.715977192779635.043265656754549.153477162779700.147432327
754067.382643878780247.022432342754507.703824371782094.678682342
754750.759379983 782591.64048788755412.651741087783225.321043447
756239.474657744783822.109237894756830.810542554784087.354177043
756972.981602162784410.216876775757550.212475032784796.018023178
758619.827463776786538.484733239758559.355668306787138.310060605

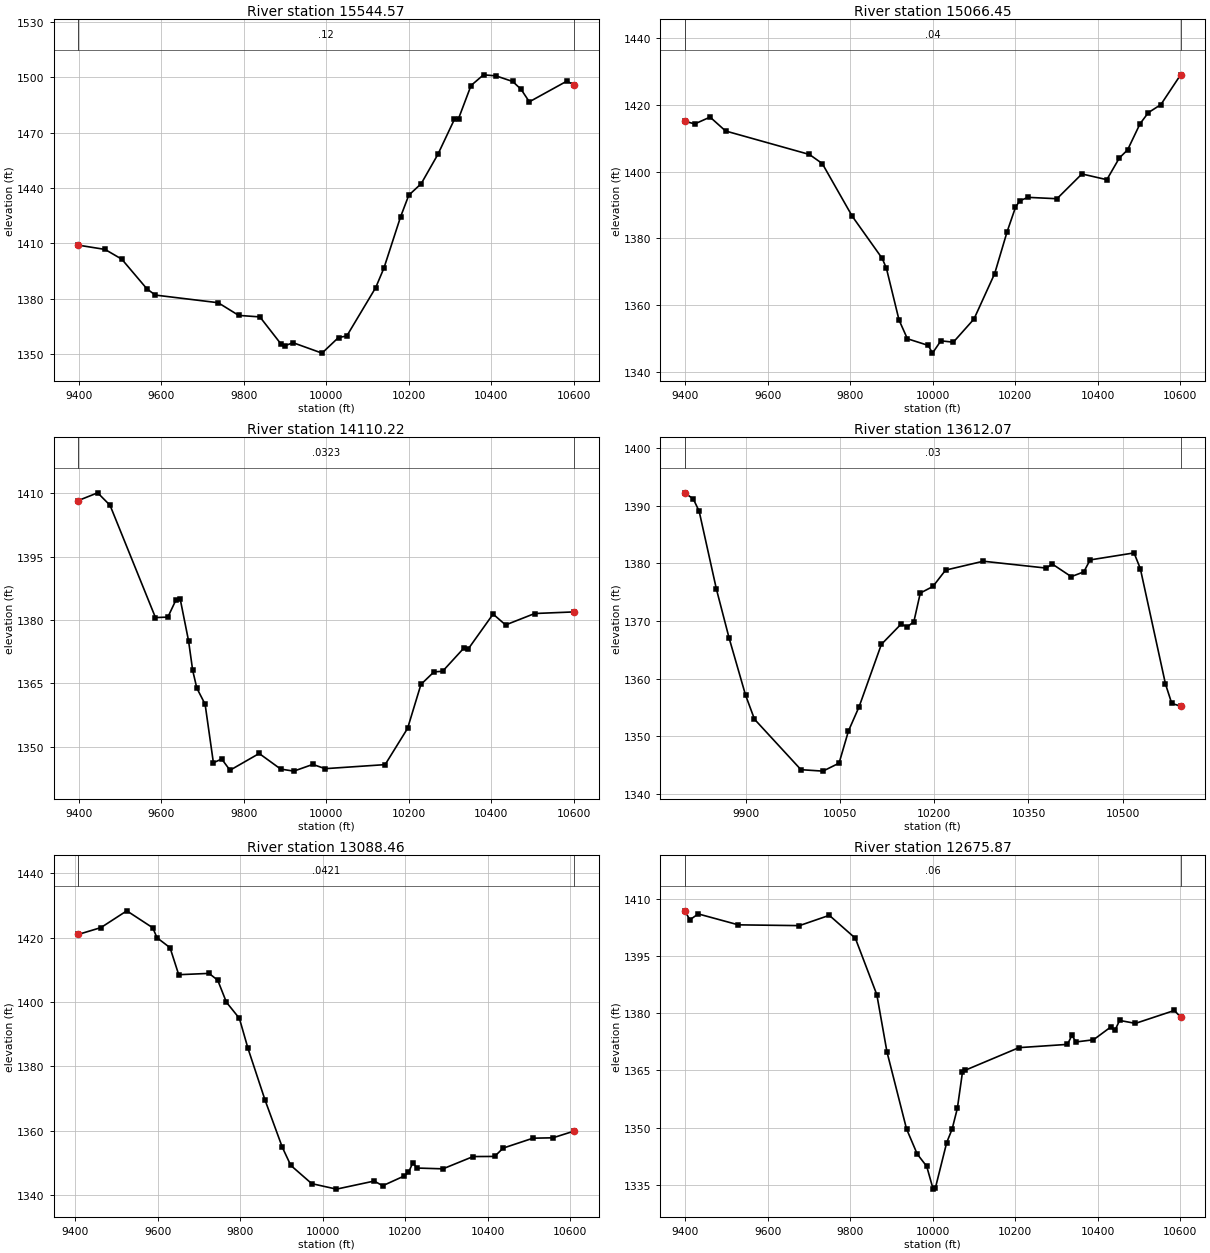
Type RM Length L Ch R = 1 ,15544.57,478.116400,478.116400,478.116400
XS GIS Cut Line= 6
759322.711491777778561.275137749759253.710087326778951.446521157
759236.816497044779131.400586095759239.140571525779243.088626757
759249.514842852779376.437948308759298.874405676779752.541917816
#Sta/Elev= 30
9399.0451409.0099463.7591406.6969504.3791401.409 9565.311385.3369585.6211381.969
9737.948 1377.839787.8641370.9549839.1681370.1449889.5621355.6789899.6051354.519
9919.636 1356.169989.7241350.52110029.741358.98610049.751359.78610119.861385.991
10139.921396.64110180.041424.267 10200.11436.07110230.221442.32110270.481458.123
10310.741477.17410320.811477.60210351.01 1495.4910381.211501.27210411.511500.709
10451.921497.66510472.121493.47110492.331486.65510583.251497.85710600.971495.832
#Mann= 3 , 0 , 0
9399.045    0.12       09399.045    0.12       010600.97    0.12       0
#XS Ineff= 2 , 0
       0                               0
Bank Sta=9399.045,10600.97
Exp/Cntr=0.3,0.1

Type RM Length L Ch R = 1 ,15066.45,956.232900,956.232900,956.232900
XS GIS Cut Line= 6
758957.579326792778511.564352094758914.683469678778702.415681924
758838.785846599778975.622436706758812.972430124779126.473561956
758820.092770164779257.839048022758872.099854609779692.607614122
#Sta/Elev= 30
9399.0581415.1979423.0031414.3549460.3631416.4079497.9531412.242 9701.161405.199
9732.2971402.4719804.9471386.6659877.5981374.0189887.8011371.0399918.3731355.542
9938.5751349.9269989.139 1347.939999.4041345.61110019.861349.30610049.961348.886
10100.031355.83810150.191369.46610180.361382.032 10200.51389.29410210.571391.267
10230.721392.33810301.221391.92410361.641399.35610422.071397.63510452.28 1404.13
10472.431406.58810502.641414.42510522.781417.756   10553 1420.1510600.941429.088
#Mann= 3 , 0 , 0
9399.058    0.04       09399.058    0.04       010600.94    0.04       0
#XS Ineff= 2 , 0
       0                               0
Bank Sta=9399.058,10600.94
Exp/Cntr=0.3,0.1

Type RM Length L Ch R = 1 ,14110.22,498.148300,498.148300,498.148300
XS GIS Cut Line= 6
758426.321247587778408.218517293758385.634641081778894.043667793
758353.163161079778963.552487043758269.305950484779015.333226171
758206.167753354779157.370297568758143.760695022779530.306526948
#Sta/Elev= 30
9399.2511408.317 9446.061410.1369476.0781407.1899586.1751380.5989616.2391380.709
9636.2811384.8719646.3021384.8939666.3451375.0929676.3661368.0889686.3871363.894
9706.4291360.0879726.5491346.2259746.6751347.111  9766.81344.4529837.4981348.418
9889.7021344.7219921.3661344.2419967.397 1345.839997.3231344.82310142.691345.781
10197.091354.36210229.481364.77510261.111367.74310281.891367.87510333.171373.342
10343.37 1373.0710404.321381.42610434.591378.85310505.12 1381.5610600.751381.943
#Mann= 3 , 0 , 0
9399.251  0.0323       09399.251  0.0323       010600.75  0.0323       0
#XS Ineff= 2 , 0
       09948.095                       0
Bank Sta=9399.251,10600.75
Exp/Cntr=0.3,0.1

Type RM Length L Ch R = 1 ,13612.07,523.613800,523.613800,523.613800
XS GIS Cut Line= 6
757818.501066939778955.192215683757872.159675343779034.256028817
757996.604823928779119.779172908 758031.12676518779176.076037807
758052.222021707779311.640784267758049.672310315779649.127740208
#Sta/Elev= 30
9802.8961392.2039816.4421391.1359825.7271389.0219853.2951375.486 9873.411367.061
9899.701 1357.139913.8561352.9839987.8211344.24510022.851343.99510048.481345.378
10063.461350.95310080.531355.18710115.831365.951 10147.2 1369.4610157.411368.989
10167.621369.90710177.791374.84110197.931375.98210218.051378.81410278.111380.355
10378.111379.16810388.111379.85410418.121377.68410438.121378.50610448.121380.581
10518.121381.79510528.121379.06510568.131359.09510578.131355.72310592.26 1355.25
#Mann= 3 , 0 , 0
9802.896    0.03       09802.896    0.03       010592.26    0.03       0
#XS Ineff= 2 , 0
       0                               0
Bank Sta=9802.896,10592.26
Exp/Cntr=0.3,0.1

Type RM Length L Ch R = 1 ,13088.46,412.587100,412.587100,412.587100
XS GIS Cut Line= 6
757293.128359597 778612.56380554757434.607137977779068.935192441
757450.726568138779144.771668007757462.532591423779286.003509569
757547.405255721779574.351848618757596.512858556779772.127448237
#Sta/Elev= 30
9407.6411421.0119462.428 1423.139525.1181428.3399587.9191423.0799598.4261419.976
9629.9461416.878 9650.961408.4929724.5081408.8999745.5211406.7849766.5351399.952
9798.0551394.9239818.912 1385.589860.5541369.4219901.994  1354.99922.5631349.254
9973.3021343.58110033.36 1341.8710124.761344.37710145.441342.92210197.481345.948
10207.931347.09710218.371349.98710228.821348.418 10291.51348.17410364.631351.989
10416.751352.02710437.411354.61810509.751357.69710558.081357.81610609.54 1359.91
#Mann= 3 , 0 , 0
9407.641  0.0421       09407.641  0.0421       010609.54  0.0421       0
#XS Ineff= 2 , 0
       0                               0
Bank Sta=9407.641,10609.54
Exp/Cntr=0.3,0.1

Type RM Length L Ch R = 1 ,12675.87,478.116400,478.116400,478.116400
XS GIS Cut Line= 6
756961.057291044 778872.96465325757059.909209411779289.070989268
757101.848424691779372.318931671 757200.71974882779482.619125651
757262.500162186779593.020532251757380.083189434779979.728439175
#Sta/Elev= 30
 9399.141406.8299411.3871404.4739431.7371406.0189528.9241403.1529676.9551402.948
 9749.371405.6489812.5091399.639 9864.531384.8479889.1331369.8379936.5191349.646
9962.4221343.0449985.4621339.816   100011333.83910006.751334.24910033.931346.058
10046.991349.56710059.681354.99610072.141364.52510077.45 1364.9610208.921370.943
10326.661371.80110337.191374.13610347.721372.445 10389.71373.00910431.141376.325
10441.491375.45510453.011378.08310491.341377.30910585.761380.69510600.871378.956
#Mann= 3 , 0 , 0
 9399.14    0.06       0 9399.14    0.06       010600.87    0.06       0
#XS Ineff= 2 , 0
       0                               0
Bank Sta=9399.14,10600.87
Exp/Cntr=0.3,0.1

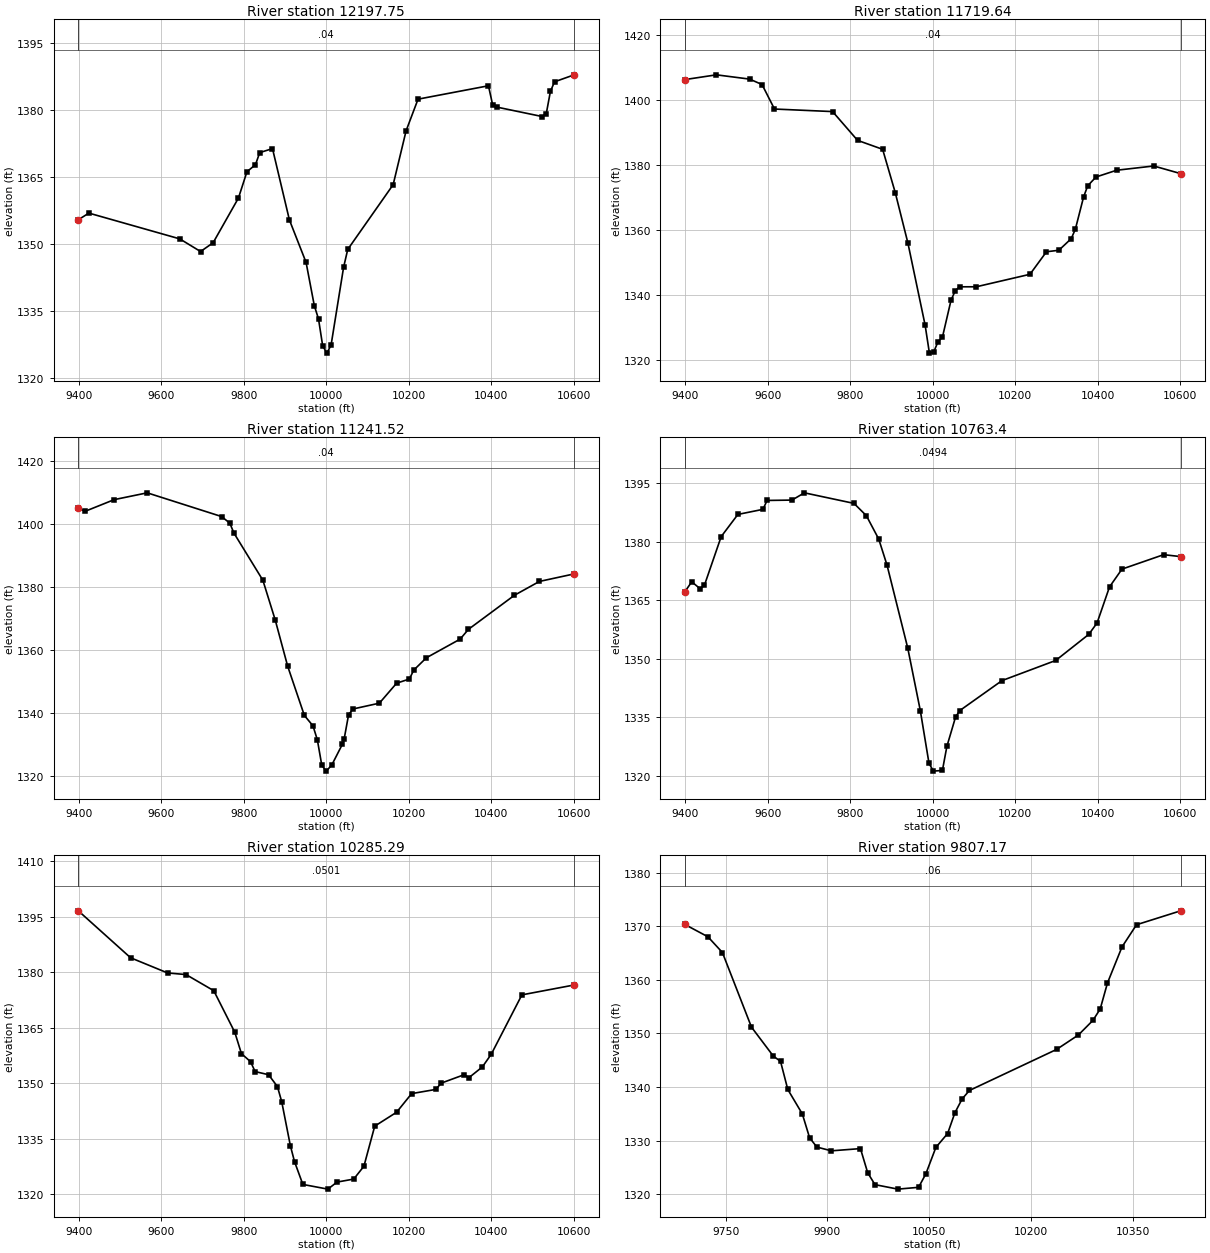
Type RM Length L Ch R = 1 ,12197.75,478.116400,478.116400,478.116400
XS GIS Cut Line= 6
756757.847458194778829.467003915756753.049507871779100.206329526
756697.362122115779363.552451221756711.512558438779524.649853391
756685.831414284779835.325778016 756681.22398406780022.594924536
#Sta/Elev= 30
9399.1821355.4299424.7381356.9159645.0031351.1559695.4681348.3249725.8821350.289
9787.2341360.283 9807.871366.1659828.505 1367.749838.8231370.4379869.7771371.342
9910.7631355.3939951.181 1345.899971.1881336.196 9981.291333.2679991.4281327.235
10001.611325.60810011.791327.41610042.091344.79110052.141348.79310162.261363.279
 10193.61375.31810222.551382.39210393.211385.38310403.24 1381.1710413.261380.621
10523.341378.50910533.341379.13710543.341384.11310553.341386.27110600.941387.832
#Mann= 3 , 0 , 0
9399.182    0.04       09399.182    0.04       010600.94    0.04       0
#XS Ineff= 2 , 0
       0                               0
Bank Sta=9399.182,10600.94
Exp/Cntr=0.3,0.1

Type RM Length L Ch R = 1 ,11719.64,478.116500,478.116500,478.116500
XS GIS Cut Line= 6
756224.111047746778678.846370947756274.116146994 779119.72290537
756294.131676991 779221.32719745756327.006981099779330.413918578
756336.981465293779397.484963484756333.746337563779870.125094329
#Sta/Elev= 30
9399.0391406.3269475.6251407.795 9556.081406.479 9586.251404.812 9616.421397.262
9757.2941396.4779817.8281387.618 9878.59 1384.869909.1391371.5569939.8721355.991
9981.554 1330.749992.0081322.09910002.461322.46410013.011325.65610023.571327.019
 10044.4  1338.410054.731341.32210064.98 1342.5210105.541342.52710235.751346.374
10275.761353.31710305.771353.77310335.781357.35410345.791360.26810365.791370.217
 10375.81373.638 10395.81376.33310445.811378.41610535.811379.72410600.941377.382
#Mann= 3 , 0 , 0
9399.039    0.04       09399.039    0.04       010600.94    0.04       0
#XS Ineff= 2 , 0
       0                               0
Bank Sta=9399.039,10600.94
Exp/Cntr=0.3,0.1

Type RM Length L Ch R = 1 ,11241.52,478.116400,478.116400,478.116400
XS GIS Cut Line= 6
755835.332031225778828.381129238755847.529119069779047.301364879
755837.249478969779348.538053162755933.282281527779641.084697989
755959.996814345779775.998420072755992.959922928780008.480340417
#Sta/Elev= 30
 9399.121405.0269415.791    1404 9486.011407.6879566.0961409.8499746.1881402.331
9766.2351400.2529776.2591397.0889846.4251382.1239876.4881369.4699906.5061354.874
9947.0141339.234  9967.91335.9449978.5381331.467 9989.271323.42310000.011321.578
10013.491323.52610039.421330.17210043.361331.716 10054.21339.47410065.041341.296
10128.831343.13110170.651349.46910201.671350.796   102121353.60110242.831357.536
 10324.51363.43810344.82 1366.5610456.191377.35610516.741381.74410600.971384.133
#Mann= 3 , 0 , 0
 9399.12    0.04       0 9399.12    0.04       010600.97    0.04       0
#XS Ineff= 2 , 0
       0                               0
Bank Sta=9399.12,10600.97
Exp/Cntr=0.3,0.1

Type RM Length L Ch R = 1 , 10763.4,478.116400,478.116400,478.116400
XS GIS Cut Line= 6
755502.689020031778708.405503573755549.574240867779090.457431674
755540.187215793 779257.15648868755495.604774386 779394.58828213
755479.126825111779523.126745507755511.678495414779895.729951969
#Sta/Elev= 30
9399.1241367.172 9416.02 1369.749436.3841367.9499446.5661368.8149487.2941381.313
9527.7961386.9969588.4681388.2949598.5791390.5779658.8661390.6689689.0051392.528
9809.1511389.8239839.158 1386.689869.1651380.6819889.2361374.0219939.4691352.778
    99701336.7199991.0341323.21910001.85 1321.2410023.521321.42210034.361327.581
10055.421335.114 10065.81336.76410167.891344.42610298.111349.58810378.231356.268
10398.331359.18710428.511368.42910458.691372.98510559.681376.68610600.871376.194
#Mann= 3 , 0 , 0
9399.124  0.0494       09399.124  0.0494       010600.87  0.0494       0
#XS Ineff= 2 , 0
       0                               0
Bank Sta=9399.124,10600.87
Exp/Cntr=0.3,0.1

Type RM Length L Ch R = 1 ,10285.29,478.116400,478.116400,478.116400
XS GIS Cut Line= 6
754914.377711242778901.856792119755126.091318687779333.312356938
755140.607510072779399.124574786755133.848136899779505.005753045
755280.143917454779711.857670179755377.808570662779986.380071684
#Sta/Elev= 30
9399.1311396.6159525.8261383.9219615.4081379.8219660.1991379.3829727.386 1375.02
9778.3031363.7869794.4071358.0139816.5051355.8289827.5541353.1549860.1321352.313
9881.636 1349.119892.0741344.9979912.9421333.1539923.0521328.8179943.2721322.647
10003.921321.37910026.131323.28510066.581324.09410091.251327.57310117.441338.402
10170.311342.15210206.951347.203 10265.8 1348.3410278.181350.018 10334.51352.326
10345.571351.49410378.291354.41410399.821357.83710474.111373.89610600.781376.567
#Mann= 3 , 0 , 0
9399.131  0.0501       09399.131  0.0501       010600.78  0.0501       0
#XS Ineff= 2 , 0
       0                               0
Bank Sta=9399.131,10600.78
Exp/Cntr=0.3,0.1

Type RM Length L Ch R = 1 , 9807.17,385.304600,385.304600,385.304600
XS GIS Cut Line= 2
754732.820170969779343.229191944754993.842109621780025.692802414
#Sta/Elev= 30
9689.7661370.3619723.8611368.0529745.1941365.118 9788.021351.1889820.1391345.793
9830.8461344.7939841.5521339.5469862.965 1334.989873.6721330.5379884.3781328.796
9905.7911328.0959948.617 1328.519959.3231323.991 9970.031321.78110003.791320.945
10034.271321.28110044.97 1323.7910059.781328.73810077.091331.327 10087.81335.198
10098.511337.79310109.211339.36410237.691347.02710269.811349.72410291.221352.449
10301.931354.57710312.641359.43210334.05 1366.1610355.461370.30310420.441372.899
#Mann= 3 , 0 , 0
9689.766    0.06       09689.766    0.06       010420.44    0.06       0
#XS Ineff= 2 , 0
       0                               0
Bank Sta=9689.766,10420.44
Exp/Cntr=0.3,0.1

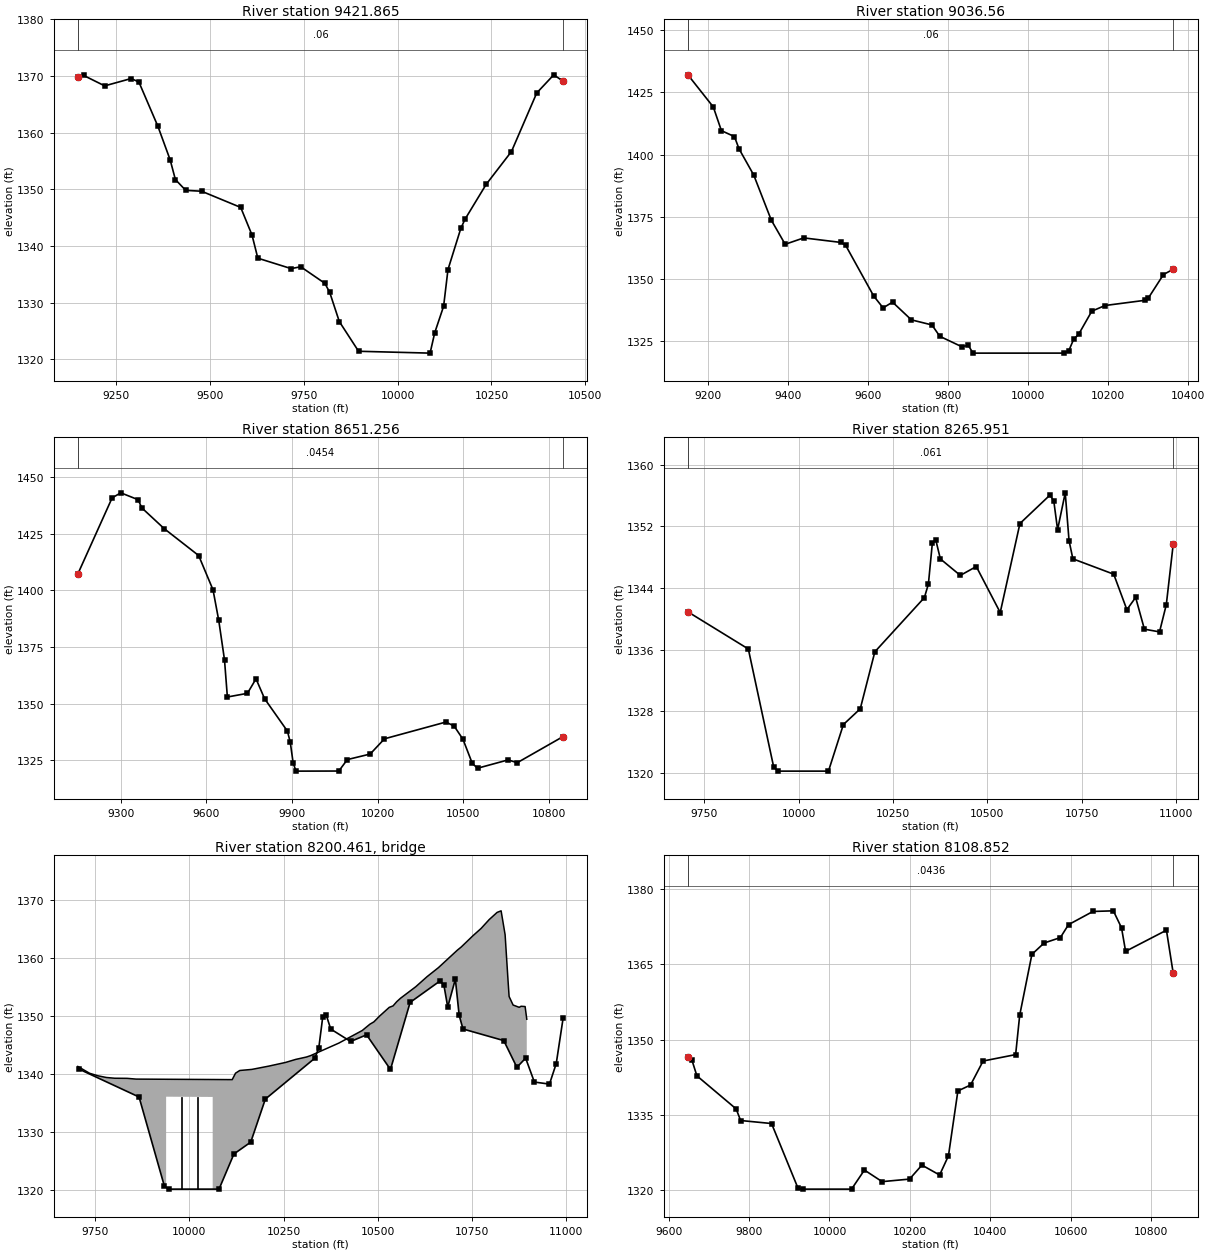
Type RM Length L Ch R = 1 ,9421.865,385.304600,385.304600,385.304600
XS GIS Cut Line= 6
753924.170638015779130.621417493754176.771923822779388.566952475
754444.705170467779710.512465371754540.660615839 779808.38116767
754588.805276946779882.668535176754720.136243458780136.774986518
#Sta/Elev= 30
9149.0471369.9229164.2871370.1279220.5811368.2759290.9471369.5679311.6021368.958
9362.217 1361.139394.9571355.1799408.7381351.7269436.3011349.8159478.4811349.661
9582.6271346.803 9612.73 1341.929628.1911337.8359716.8081335.9949742.4571336.317
 9806.581333.3949819.4051331.8189845.0541326.6419896.353 1321.39 10086.71321.062
10099.011324.65310122.671329.337 10134.3 1335.8210168.531343.108 10179.9 1344.74
10235.991350.878 10303.31356.679 10370.61367.02610415.871370.22510440.931369.088
#Mann= 3 , 0 , 0
9149.047    0.06       09149.047    0.06       010440.93    0.06       0
#XS Ineff= 2 , 0
       0                               0
Bank Sta=9149.047,10440.93
Exp/Cntr=0.3,0.1

Type RM Length L Ch R = 1 , 9036.56,385.304600,385.304600,385.304600
XS GIS Cut Line= 6
753493.804902199779573.582280465753679.801119111779679.361897469
753996.101443804779870.623711475754252.833385711  780035.6750636
754348.873845659780102.570669926754514.493233564 780227.93632081
#Sta/Elev= 30
9149.0091432.0889212.5611419.1699232.7891409.6569265.4241407.2469276.9281402.326
9313.7011391.7849357.4571373.7049392.2651363.9649438.7511366.5349531.7231364.709
9543.345 1363.589613.623 1343.169637.1651338.3979660.7081340.7119707.7931333.584
9759.2431331.5369778.8561326.9719833.2851322.8279850.1561323.3099862.0391320.207
10089.231320.21610101.421321.179 10113.61325.78310125.791327.70310158.911337.067
10192.05 1339.3510291.461341.43310300.531342.39810338.15  1351.8 10362.61353.938
#Mann= 3 , 0 , 0
9149.009    0.06       09149.009    0.06       0 10362.6    0.06       0
#XS Ineff= 2 , 0
       0                               0
Bank Sta=9149.009,10362.6
Exp/Cntr=0.3,0.1

Type RM Length L Ch R = 1 ,8651.256,385.304600,385.304600,385.304600
XS GIS Cut Line= 6
753216.464494091780257.463401598753752.499338288780337.095764653
754248.012349862780356.286906462754390.628866553780373.212016389
754637.108762254780435.657814129754881.602658029780538.864753941
#Sta/Elev= 30
9149.0261407.1959269.3961440.8249299.8171443.0359360.5721439.9979373.3921436.397
9451.6811427.2569572.8091415.3549623.1361400.2149643.2671386.6979663.3981369.314
9673.4641352.9229743.7781354.5439773.8921360.9479803.9511352.1749884.057 1337.86
9894.0621332.8869904.0671323.8379914.0721320.20710064.151320.24810094.151325.304
10174.181327.74410224.341334.47210439.481341.85910468.461340.12210499.551334.273
10532.241323.62910550.641321.48410657.711325.15610690.011323.93310850.94 1335.48
#Mann= 3 , 0 , 0
9149.026  0.0454       09149.026  0.0454       010850.94  0.0454       0
#XS Ineff= 2 , 0
       0                 10242.5       0
Bank Sta=9149.026,10850.94
Exp/Cntr=0.3,0.1

Type RM Length L Ch R = 1 ,8265.951,157.099600,157.099600,157.099600
XS GIS Cut Line= 5
753871.676917911780859.346469805754388.343584567780601.013136476
754630.010251224780517.679803148754867.510251224780555.179803133
755050.843584567780663.513136476
#Sta/Elev= 30
9706.0071340.8949866.2471336.0679933.3291320.7699944.5091320.20710078.671320.207
10118.221326.25610162.941328.30110201.661335.70410333.011342.74410343.591344.506
10354.171349.87710363.461350.17110375.321347.76510428.211345.62410470.521346.774
10533.991340.80310586.221352.35810665.831356.05410675.951355.30310686.071351.563
10706.321356.34710716.451350.12910726.571347.77610834.89 1345.7810869.741341.173
10892.971342.763 10916.2 1338.6410956.29 1338.2910974.281341.83110992.681349.713
#Mann= 3 , 0 , 0
9706.007   0.061       09706.007   0.061       010992.68   0.061       0
#XS Ineff= 2 , 0
       0                10141.32       0
Bank Sta=9706.007,10992.68
Exp/Cntr=0.3,0.1

Type RM Length L Ch R = 3 ,8200.461,,,
BEGIN DESCRIPTION:
END DESCRIPTION:
Bridge Culvert--1,0,-1,-1, 0
Deck Dist Width WeirC Skew NumUp NumDn MinLoCord MaxHiCord MaxSubmerge Is_Ogee
67.066900,22.965800,2.6,0, 47, 47, , , 0.95, 0, 0,0,,
 9703.60 9734.96 9757.11 9779.26 9801.40 9834.62 9858.51 9938.16 9938.1610061.84
10061.8410113.6910122.5210133.5910165.8610211.1110255.4010282.2910310.7610321.84
10396.9210458.8610479.5110489.8410504.7610530.7110540.7610550.8110560.8710601.07
10631.2310661.3810711.6410721.6910753.4710774.7210795.9710817.2210827.8410838.47
10846.1710849.0910859.7210875.7610880.9710891.5910896.03
 1341.33 1340.15 1339.72 1339.43 1339.30 1339.28 1339.15 1339.12 1339.12 1339.08
 1339.08 1339.06 1340.17 1340.63 1340.82 1341.39 1342.02 1342.54 1342.95 1343.19
 1345.35 1347.51 1348.61 1349.00 1349.98 1351.50 1351.75 1352.49 1353.08 1355.05
 1356.79 1358.34 1361.35 1361.88 1363.86 1365.09 1366.60 1367.85 1368.12 1364.01
 1356.20 1353.37 1351.90 1351.51 1351.69 1351.64 1349.46
  341.33  340.15  339.72  339.43  339.30  339.28  339.15  339.12 1336.12 1336.08
  339.08  339.06  340.17  340.63  340.82  341.39  342.02  342.54  342.95  343.19
  345.35  347.51  348.61  349.00  349.98  351.50  351.75  352.49  353.08  355.05
  356.79  358.34  361.35  361.88  363.86  365.09  366.60  367.85  368.12  364.01
  356.20  353.37  351.90  351.51  351.69  351.64  349.46
 9703.60 9734.96 9757.11 9779.26 9801.40 9834.62 9858.51 9938.16 9938.1610061.84
10061.8410113.6910122.5210133.5910165.8610211.1110255.4010282.2910310.7610321.84
10396.9210458.8610479.5110489.8410504.7610530.7110540.7610550.8110560.8710601.07
10631.2310661.3810711.6410721.6910753.4710774.7210795.9710817.2210827.8410838.47
10846.1710849.0910859.7210875.7610880.9710891.5910896.03
 1341.33 1340.15 1339.72 1339.43 1339.30 1339.28 1339.15 1339.12 1339.12 1339.08
 1339.08 1339.06 1340.17 1340.63 1340.82 1341.39 1342.02 1342.54 1342.95 1343.19
 1345.35 1347.51 1348.61 1349.00 1349.98 1351.50 1351.75 1352.49 1353.08 1355.05
 1356.79 1358.34 1361.35 1361.88 1363.86 1365.09 1366.60 1367.85 1368.12 1364.01
 1356.20 1353.37 1351.90 1351.51 1351.69 1351.64 1349.46
  341.33  340.15  339.72  339.43  339.30  339.28  339.15  339.12 1336.12 1336.08
  339.08  339.06  340.17  340.63  340.82  341.39  342.02  342.54  342.95  343.19
  345.35  347.51  348.61  349.00  349.98  351.50  351.75  352.49  353.08  355.05
  356.79  358.34  361.35  361.88  363.86  365.09  366.60  367.85  368.12  364.01
  356.20  353.37  351.90  351.51  351.69  351.64  349.46
Pier Skew, UpSta & Num, DnSta & Num=  ,9978.89, 2 ,9978.89, 2 , 0 , 0 , 0 ,,
    3.00    3.00
  339.11 1339.11
    3.00    3.00
  339.11 1339.11
Pier Skew, UpSta & Num, DnSta & Num=  ,10021.11, 2 ,10021.11, 2 , 0 , 0 , 0 ,,
    3.00    3.00
  339.09 1339.09
    3.00    3.00
  339.09 1339.09
BR Coef=-1 , 0 , 0 ,, 0 ,,,0.8,0,1,0,
WSPro=,,,, 1 ,,,, 0 ,,,, 0 ,,,,-1 ,-1 ,-1 , 0 , 0 , 0 , 0 , 0
BC Design=,, 0 ,, 0 ,,,,,,

Type RM Length L Ch R = 1 ,8108.852,961.154100,961.154100,961.154100
XS GIS Cut Line= 5
753884.777632775781010.503344763753896.676917911 781009.34646982
754534.176917911780717.679803163754809.176917881780676.013136476
755021.676917881780713.513136476
#Sta/Elev= 30
9647.9681346.4379658.2381345.853 9670.37 1342.789768.0481336.1829779.0451333.876
9856.0241333.2769922.0051320.3549933.0021320.20710054.951320.20710086.961324.011
10130.951321.69810199.161322.20710229.921324.99410273.911323.021 10295.91326.845
10319.351339.76710350.881340.95110382.041345.72910462.951347.00810473.06 1354.85
10503.411366.97910533.75 1369.2410574.21 1370.3210594.431372.89510655.181375.525
10705.961375.65110726.26 1372.2710736.42 1367.5810837.961371.787 10854.91363.175
#Mann= 3 , 0 , 0
9647.968  0.0436       09647.968  0.0436       0 10854.9  0.0436       0
#XS Ineff= 2 , 0
       0                10141.05       0
Bank Sta=9647.968,10854.9
Exp/Cntr=0.3,0.1

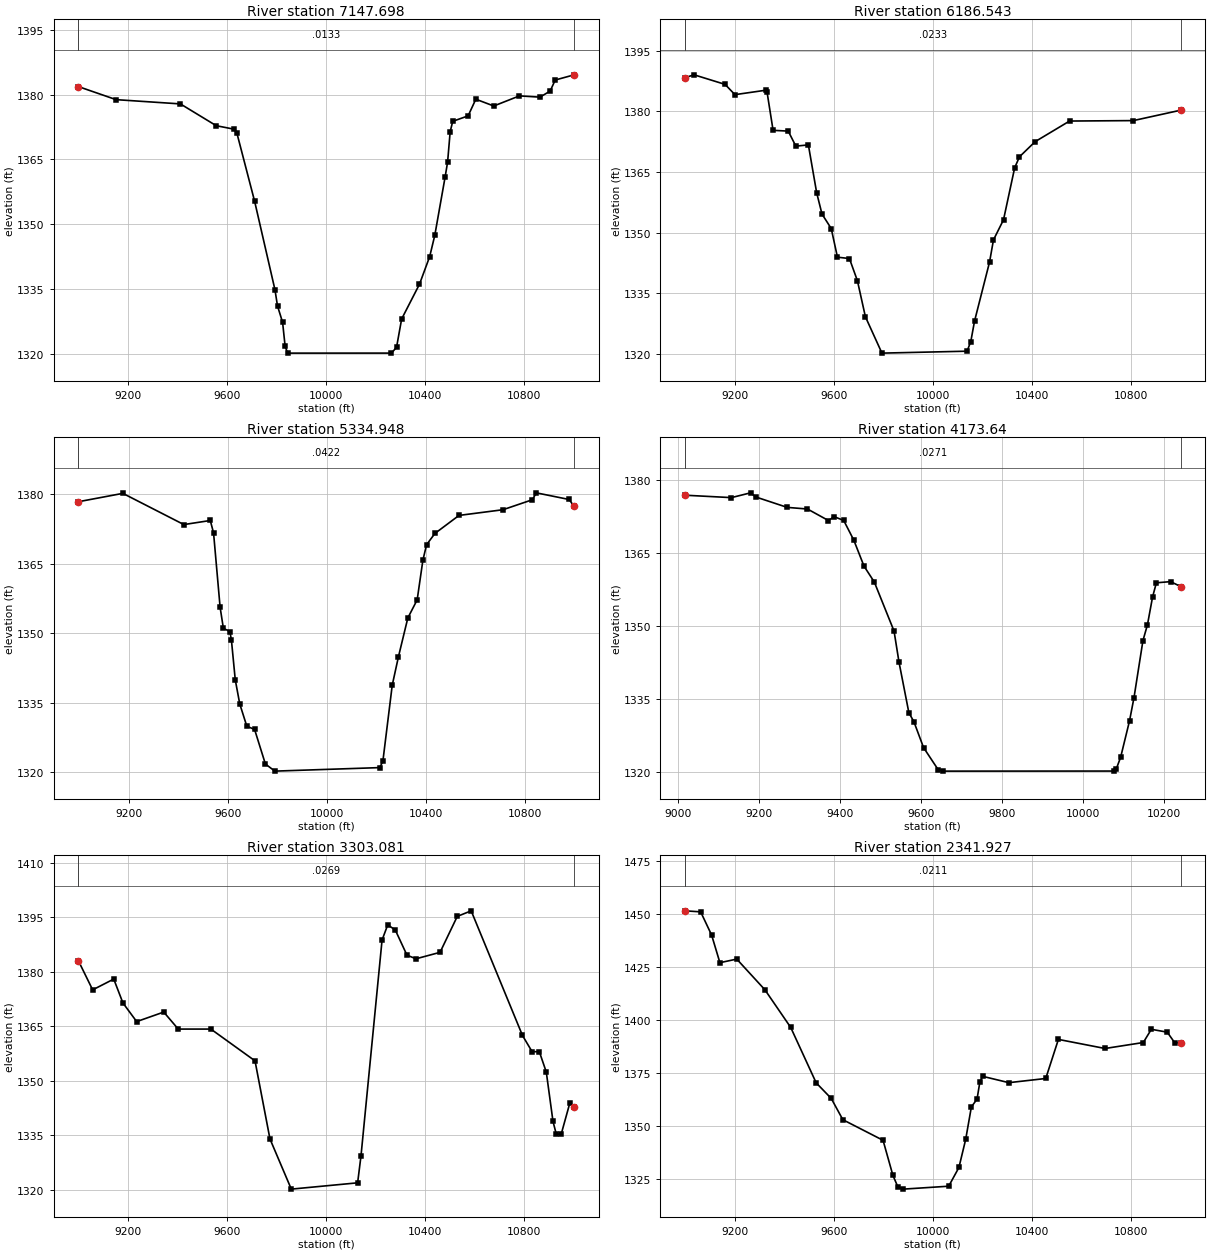
Type RM Length L Ch R = 1 ,7147.698,961.154100,961.154100,961.154100
XS GIS Cut Line= 6
753477.932312808782042.952426199 754123.53145971781867.020164002
754299.685566396781825.659816846754770.840746781781725.156820433
755279.009568806781590.319297116755419.224162928781556.115810832
#Sta/Elev= 30
8999.0131381.8549151.6321378.8289411.0691377.8459555.9631372.8029628.3331371.992
9638.6711371.2119710.7651355.332 9792.941334.8549803.2121331.1169823.7561327.327
9834.0281321.761  9844.31320.20710263.371320.21210283.881321.56310304.39  1328.1
10376.451336.14510417.721342.54610438.351347.47910479.621360.83510489.961364.372
10500.321371.39710510.681373.81810572.831375.079 10603.91378.93310676.411377.362
   107801379.70110862.821379.411   109041380.81310924.581383.37111000.98 1384.57
#Mann= 3 , 0 , 0
8999.013  0.0133       08999.013  0.0133       011000.98  0.0133       0
#XS Ineff= 2 , 0
       0                               0
Bank Sta=8999.013,11000.98
Exp/Cntr=0.3,0.1

Type RM Length L Ch R = 1 ,6186.543,851.595600,851.595600,851.595600
XS GIS Cut Line= 6
754028.406868281783265.532064209 754534.56037887 782915.46199718
754719.008850702782764.760786004755069.696650817782440.471640689
755370.571688083782212.958487893755613.876435643782050.075396777
#Sta/Elev= 30
8999.0361388.3279036.806 1389.039161.7741386.6659201.4111384.126 9325.741385.221
9331.0351384.8059355.4941375.303 9416.641375.1139447.3441371.395 9497.98  1371.7
9531.5321359.842 9552.911354.6059590.2741351.0199615.3811343.9369663.7391343.594
9695.9781338.1089728.2171329.2069795.0231320.20710138.651320.68710153.781323.079
10168.911328.13910229.551342.74510245.251348.19710285.88 1353.1910330.881366.034
10350.27 1368.7610413.631372.50710552.561377.60210810.071377.71111000.96 1380.28
#Mann= 3 , 0 , 0
8999.036  0.0233       08999.036  0.0233       011000.96  0.0233       0
#XS Ineff= 2 , 0
       0                               0
Bank Sta=8999.036,11000.96
Exp/Cntr=0.3,0.1

Type RM Length L Ch R = 1 ,5334.948,1161.308000,1161.308000,1161.308000
XS GIS Cut Line= 6
754783.194869281784001.983935375754999.541757004783781.595251027
755230.630993108783520.575119031755762.657950874782825.122361557
755919.694414673782635.032828748756068.466311555782470.129549167
#Sta/Elev= 30
8996.2721378.394 9176.011380.2039422.3641373.4629529.0431374.3449542.2531371.664
9568.6721355.6159581.8821351.0569608.3021350.3589614.5481348.4259629.8531339.943
9647.9311334.7449676.4411329.9169707.9881329.204  9751.51321.749 9789.741320.207
10213.541320.96810225.971322.37910263.711338.77510288.871344.93910326.611353.284
10364.391357.20910387.63 1365.8310402.541369.13410436.191371.55510533.26 1375.44
10710.87 1376.6710829.831378.83510845.05 1380.3210978.03 1378.8810998.221377.373
#Mann= 3 , 0 , 0
8996.272  0.0422       08996.272  0.0422       010998.22  0.0422       0
#XS Ineff= 2 , 0
       0                               0
Bank Sta=8996.272,10998.22
Exp/Cntr=0.3,0.1

Type RM Length L Ch R = 1 , 4173.64,870.558600,870.558600,870.558600
XS GIS Cut Line= 6
755849.855601184784698.168644647756053.572253425 784455.48483081
 756152.36685646784324.917518386756243.705800588784191.756010366
756346.990603516784014.870977615756506.378293451783671.673373692
#Sta/Elev= 30
9016.2711376.8319131.4091376.3339178.8361377.3189192.0341376.4579269.435 1374.33
9319.5421373.9949371.3881371.6289385.2451372.4299409.0081371.6579434.0881367.592
9459.1681362.2829484.6831359.0139533.4811348.9439545.7111342.577 9570.171332.172
  9582.41330.3819606.4591325.0319642.4811320.5119654.4881320.20710076.991320.221
10082.621320.627 10093.51323.04310115.541330.538 10126.61335.312 10148.71347.002
10159.761350.22110172.441355.93410181.871358.85510217.051359.09410241.811358.095
#Mann= 3 , 0 , 0
9016.271  0.0271       09016.271  0.0271       010241.81  0.0271       0
#XS Ineff= 2 , 0
       0                               0
Bank Sta=9016.271,10241.81
Exp/Cntr=0.3,0.1

Type RM Length L Ch R = 1 ,3303.081,961.154100,961.154100,961.154100
XS GIS Cut Line= 6
756334.257534259785172.904504885756821.804444926784658.889311493
 756945.51607678784516.500988927 757036.58929753  784392.5966384
757096.793968439784324.576382112757718.176865922783730.005327119
#Sta/Elev= 30
 8999.021383.0289056.8611374.9929142.0411377.9589179.0481371.3939234.5991366.265
9343.8931368.8879402.415 1364.219534.156 1364.219712.3871355.4729772.7341334.007
9858.8711320.20710126.71 1321.9410140.31 1329.3510225.361388.68810248.361392.878
10278.931391.42910325.841384.54110362.281383.52910459.51 1385.3110528.971395.184
10585.18 1396.72 10792.31362.45110831.221357.98510860.381357.99810888.481352.381
10915.551338.80710929.071335.25610948.971335.39510983.151343.79611000.971342.659
#Mann= 3 , 0 , 0
 8999.02  0.0269       0 8999.02  0.0269       011000.97  0.0269       0
#XS Ineff= 2 , 0
       0                               0
Bank Sta=8999.02,11000.97
Exp/Cntr=0.3,0.1

Type RM Length L Ch R = 1 ,2341.927,0.000000,0.000000,0.000000
XS GIS Cut Line= 6
756827.284372454785558.045824838757108.829711832785414.248974921
757549.976344803785149.594423639758207.320504764784776.815643149
758428.512498312784667.069175143758586.163618851   784607.589486
#Sta/Elev= 30
8999.0331451.6939063.0311451.2169107.3861440.2299140.7381427.1939208.8061428.891
9322.4071414.3999426.7521396.5879529.4861370.4219590.3161363.0559637.2031353.002
9799.4961343.2779839.1091326.7659859.5571321.1839881.3331320.20710064.591321.587
10105.831330.436 10133.21343.74710156.071359.03210179.031362.75210190.591370.974
10202.151373.48510307.421370.50610456.39 1372.4810507.461390.94210695.791386.654
10850.261389.47210882.731395.71610946.941394.36710978.671389.11511000.981389.479
#Mann= 3 , 0 , 0
8999.033  0.0211       08999.033  0.0211       011000.98  0.0211       0
#XS Ineff= 2 , 0
       0                               0
Bank Sta=8999.033,11000.98
Exp/Cntr=0.3,0.1